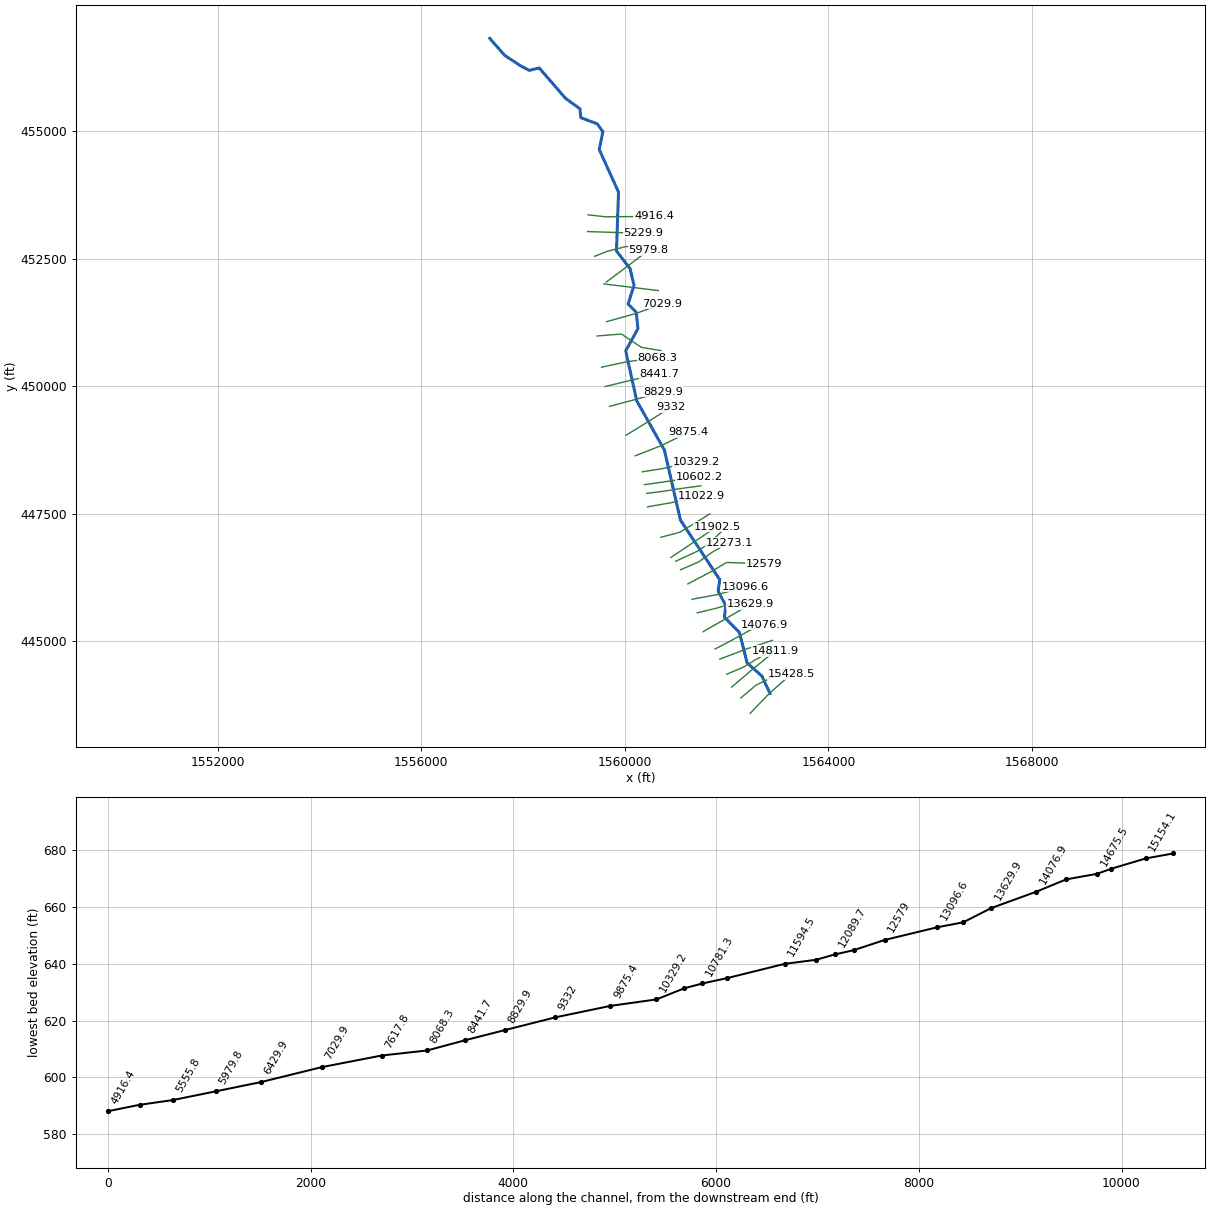
--- WILSONCR.prj (project) ---

Proj Title=WILSONCR
Current Plan=p01
Default Exp/Contr=0,0
English Units
Geom File=g01
Flow File=f01
Plan File=p01
BEGIN DESCRIPTION:
END DESCRIPTION:
DSS Export Rating Curves= 0
DSS Export Rating Curve Sorted= 0
DSS Export Volume Flow Curves= 0
DXF OffsetX= 0
DXF OffsetY= 0
DXF ScaleX= 0
DXF ScaleY= 0

--- WILSONCR.p01 (plan) ---

Plan Title=Floodplain
Program Version=4.00
Geom File=g01
Flow File=f01
K Sum by GR=0
Std Step Tol=0.01
Critical Tol=0.01
Num of Std Step Trials=20
Max Error Tol=0.3
Flow Tol Ratio=0.001
Split Flow NTrial=30
Split Flow Tol=0.02
Split Flow Ratio=0.02
Log Output Level=0
Friction Slope Method=1
Unsteady Friction Slope Method=2
Unsteady Bridges Friction Slope Method=1
Global Log Level=0
CheckData=False
Run HTab=0
Run UNet=0
Run PostProcess=0
UNET Theta=0
UNET Theta Warmup=0
UNET ZTol=0
UNET ZSATol=0
UNET MxIter=0
UNET MaxInSteps=0
UNET DtIC=0
UNET DtMin=0
UNET MaxCRTS=0
UNET WFStab=0
UNET SFStab=0
UNET WFX=0
UNET SFX=0
UNET DSS MLevel=0
UNET DZMax Abort=0
UNET Convert EG Bridges=0
UNET Use Existing IB Tables=0
UNET Froude Limit=0
UNET Froude Power=0
Write IC File=0
Echo Input=False
Echo Output=False
Write Detailed=0

--- WILSONCR.f01 (steady flow) ---

Flow Title=NFF Regression Equation
Program Version=4.00
Number of Profiles= 1
Profile Names=P100yr
River Rch & RM=WILSONCR,Main            ,15428.5
     360
River Rch & RM=WILSONCR,Main            ,14675.5
     397
River Rch & RM=WILSONCR,Main            ,14076.9
     415
River Rch & RM=WILSONCR,Main            ,12579
     442
River Rch & RM=WILSONCR,Main            ,12273.1
     648
River Rch & RM=WILSONCR,Main            ,10781.3
     689
River Rch & RM=WILSONCR,Main            ,9875.4
     765
River Rch & RM=WILSONCR,Main            ,8068.3
     822
River Rch & RM=WILSONCR,Main            ,5979.8
     896
River Rch & RM=WILSONCR,Main            ,2350.6
     988
River Rch & RM=WILSONCR,Main            ,2029.5
    1580
Boundary for River Rch & Prof#=WILSONCR,Main            , 1
Up Type= 0
Dn Type= 3
Dn Slope=0.0022
DSS Import GetInterval= 0
DSS Import GetPeak= 0
DSS Import FillOption= 0

--- WILSONCR.g01 (geometry) ---

Geom Title=USGS 10m DEM
Program Version=4.00

River Reach=WILSONCR        ,Main
Reach XY= 30
     1562852.078      443973.452     1562694.104      444312.534
     1562402.025      444573.101      1562251.78      445169.551
      1561957.73      445467.273     1561982.258      445698.286
     1561833.148      445979.998     1561865.782      446202.401
     1561091.855      447374.285     1560777.164      448746.488
     1560234.472      449710.457      1560016.78      450692.404
     1560257.851      451124.985     1560223.717      451449.025
     1560064.658      451609.346     1560180.952      451973.205
     1560102.904      452303.596     1559836.161      452648.118
     1559876.153      453803.898     1559498.299      454634.459
     1559568.572       454986.75     1559458.507      455140.768
     1559134.981       455262.78     1559117.509      455438.513
     1558836.703      455639.057     1558318.729      456237.169
     1558121.216      456189.845     1557955.592      456277.751
     1557639.544      456483.613     1557345.949      456817.954

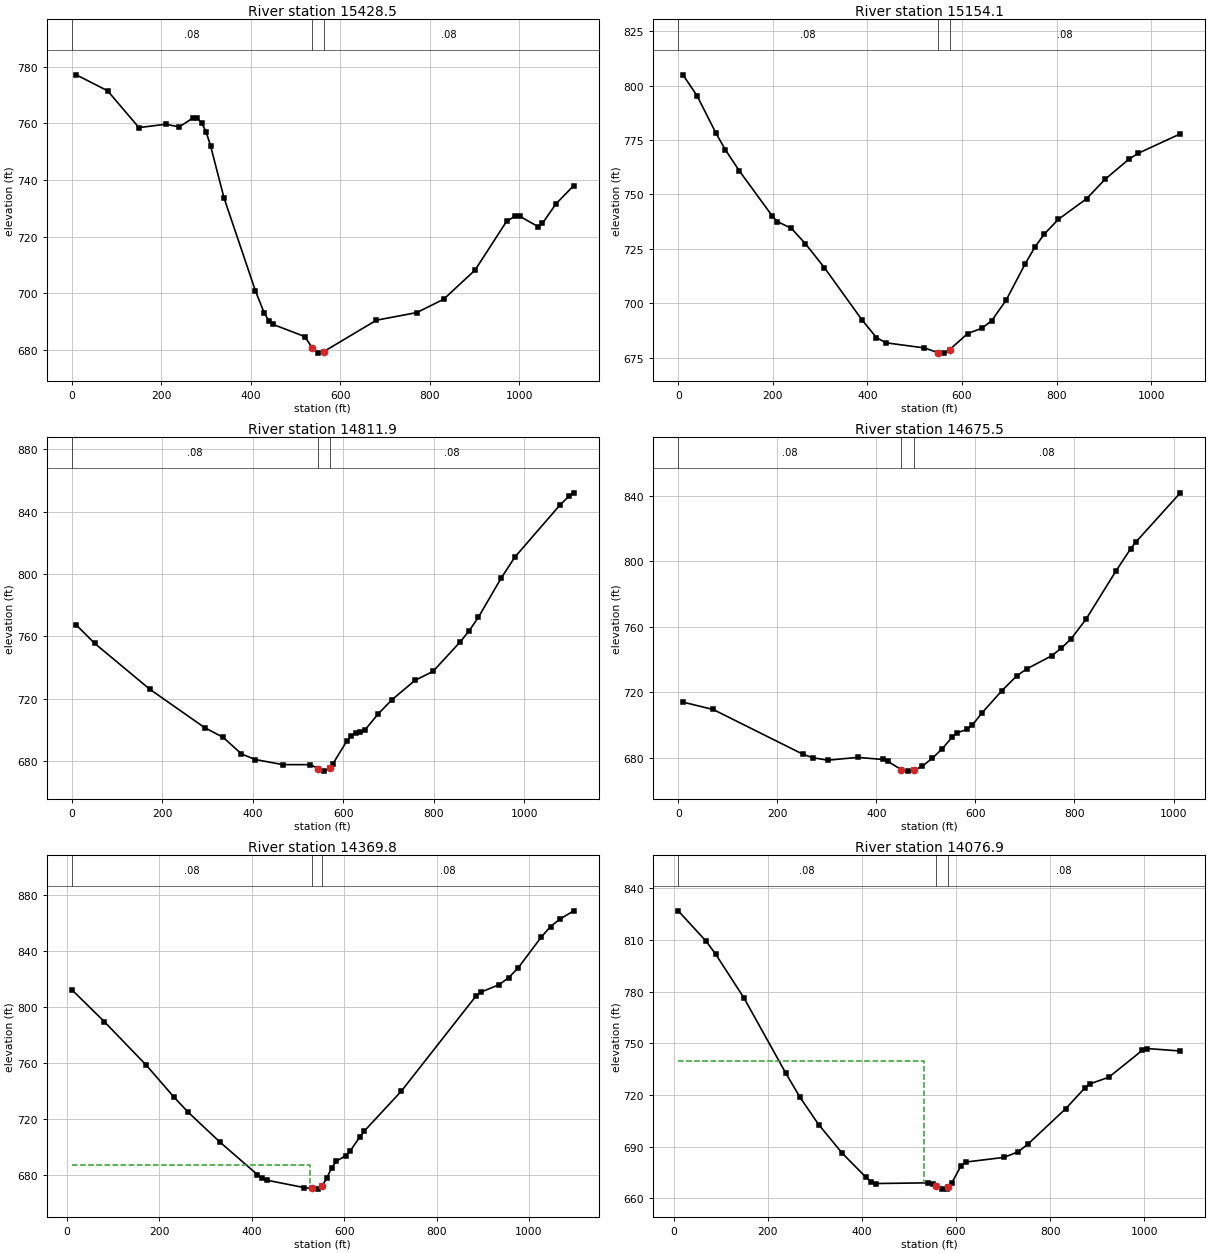
Type RM Length L Ch R = 1 ,15428.5 ,284.5,274.4,266.8
XS GIS Cut Line= 3
     1562461.429      443582.999     1562843.706       443978.92
     1563274.006      444355.221
#Sta/Elev= 30
      10  777.17    80.1  771.53   150.1  758.54   210.1  759.72   240.2  758.78
   270.2  761.87   280.2  761.82   290.2   760.2   300.2  757.04   310.2  752.08
   340.2  733.72   410.3  700.95   430.3  692.99   440.3  690.34   450.3  689.01
   520.3  684.77   537.9  680.73   550.4   678.9   562.9  679.41   680.7  690.52
     771  693.22   831.2  697.94   901.4  708.25   971.6  725.42   991.6  727.35
  1001.6  727.18  1041.8  723.59  1051.8  724.71  1081.9  731.59    1122  738.09
#Mann= 3 , 0 , 0
       0     .08       0   537.9    .045       0   562.9     .08       0
Bank Sta=537.9,562.9
XS Rating Curve= 0 ,0
Exp/Cntr=0.3,0.1

Type RM Length L Ch R = 1 ,15154.1 ,335.3,342.1,348.6
XS GIS Cut Line= 4
     1562281.326      443887.789     1562579.189      444137.162
     1562908.223      444296.484     1563164.523      444466.197
#Sta/Elev= 30
      10  804.91    39.8  795.29    79.7  778.15    99.6  770.49   129.5  760.71
   199.2  739.96   209.2  737.56   239.1  734.44   268.9  727.35   308.8  716.42
   388.5  692.37   418.9  684.28   439.2  681.86   520.5   679.5   548.6   677.4
   561.1  677.12   573.6  678.67   611.9  686.13   642.3  688.57   662.7  692.03
   693.1  701.41   733.7  718.21     754   725.8   773.9  731.82   803.6  738.55
   863.1  747.99   902.8  757.04   952.4  766.11   972.2  768.87  1061.4  777.81
#Mann= 3 , 0 , 0
       0     .08       0   548.6    .045       0   573.6     .08       0
Bank Sta=548.6,573.6
XS Rating Curve= 0 ,0
Exp/Cntr=0.3,0.1

Type RM Length L Ch R = 1 ,14811.9 ,140.1,136.4,132
XS GIS Cut Line= 3
     1562096.935      444097.494     1562514.804       444451.29
      1562952.16       444805.08
#Sta/Elev= 30
    10.1  767.25    50.7  755.48   172.4  726.08     294  701.35   334.6  695.18
   375.2  684.51   405.6  680.92   466.4  677.64   527.2  677.62   545.1   675.1
   557.6  673.46   570.1  675.52   577.7  678.31   607.8  692.66   617.8  696.24
   627.9  698.17   637.9  698.43     648  699.83   678.1   710.4   708.3  719.39
   758.5  731.66   798.7  737.52   858.9  756.45     879  763.73   899.1  772.29
   949.3  797.35   979.5  810.84  1079.9   844.5    1100   850.2  1110.1  852.17
#Mann= 3 , 0 , 0
       0     .08       0   545.1    .045       0   570.1     .08       0
Bank Sta=545.1,570.1
XS Rating Curve= 0 ,0
Exp/Cntr=0.3,0.1

Type RM Length L Ch R = 1 ,14675.5 ,311.3,305.8,300.7
XS GIS Cut Line= 4
     1562004.244      444351.901     1562347.133      444497.368
      1562551.48      444625.519     1562901.296      444819.476
#Sta/Elev= 30
    10.1  713.82    70.5  709.37   251.7  682.03   271.8  679.89     302   678.4
   362.4  680.11   412.7  678.85   422.7  677.76   450.4  672.61   462.9  671.71
   475.4  672.15   493.1  674.78   513.2  679.64   533.3  685.48   553.4  692.63
   563.4  695.15   583.5  697.26   593.6  699.83   613.7  707.42   653.7  720.94
   683.7  729.96   703.7  734.18   753.7  742.12   773.7  746.89   793.7  752.73
   823.7   764.7   883.7  793.95   913.7  807.69   923.7   811.6  1013.7  841.75
#Mann= 3 , 0 , 0
       0     .08       0   450.4    .045       0   475.4     .08       0
Bank Sta=450.4,475.4
XS Rating Curve= 0 ,0
Exp/Cntr=0.3,0.1

Type RM Length L Ch R = 1 ,14369.8 ,289,292.8,297.3
XS GIS Cut Line= 3
     1561865.842      444646.728     1562382.228      444843.263
     1562899.313      445014.971
#Sta/Elev= 30
      10  812.36    80.4  789.53   170.8  758.58   231.1  735.64   261.2  725.03
   331.5  703.18   411.9  680.15   421.9   677.6     432  676.16   512.3   670.9
     530  670.19   542.5  669.74   552.5  672.06   562.6  677.91   572.7  684.79
   582.8  689.71     603  693.59   613.1  697.03   633.2  706.77   643.3  711.15
     724   739.9   885.5  807.85   895.6  810.55   935.9  815.96   956.1  820.94
   976.3  827.73  1026.7  849.89  1046.9  857.48  1067.1  862.85  1097.4  868.74
#Mann= 3 , 0 , 0
      10     .08       0     530    .045       0   552.5     .08       0
#XS Ineff= 2 , 0
          526.31  687.28
Permanent Ineff=
       F       F
Bank Sta=530,552.5
XS Rating Curve= 0 ,0
Exp/Cntr=0.3,0.1

Type RM Length L Ch R = 1 ,14076.9 ,446.4,447,448
XS GIS Cut Line= 4
     1561772.189       444843.72     1562063.124      444996.115
     1562461.429      445214.317     1562735.047      445321.686
#Sta/Elev= 30
      10  826.92    69.7  809.13    89.6  801.74   149.3   776.5   238.9  732.52
   268.7  718.68   308.5   702.8   358.7  686.15   409.2  672.19   419.3  669.82
   429.4  668.67   540.4  669.07   550.5  668.66   558.1  667.48   570.6  665.42
   580.7  665.67   583.1  666.44   590.8  668.91     611   679.1   621.1  681.14
   701.9  683.84   732.1  687.08   752.3   691.4   833.3  712.16   873.8  724.17
   883.9  726.44   924.5  730.33   995.4  745.88  1005.6  747.02  1076.5  745.58
#Mann= 3 , 0 , 0
      10     .08       0   558.1    .045       0   583.1     .08       0
#XS Ineff= 2 , 0
          531.47  739.78
Permanent Ineff=
       F       F
Bank Sta=558.1,583.1
XS Rating Curve= 0 ,0
Exp/Cntr=0.3,0.1

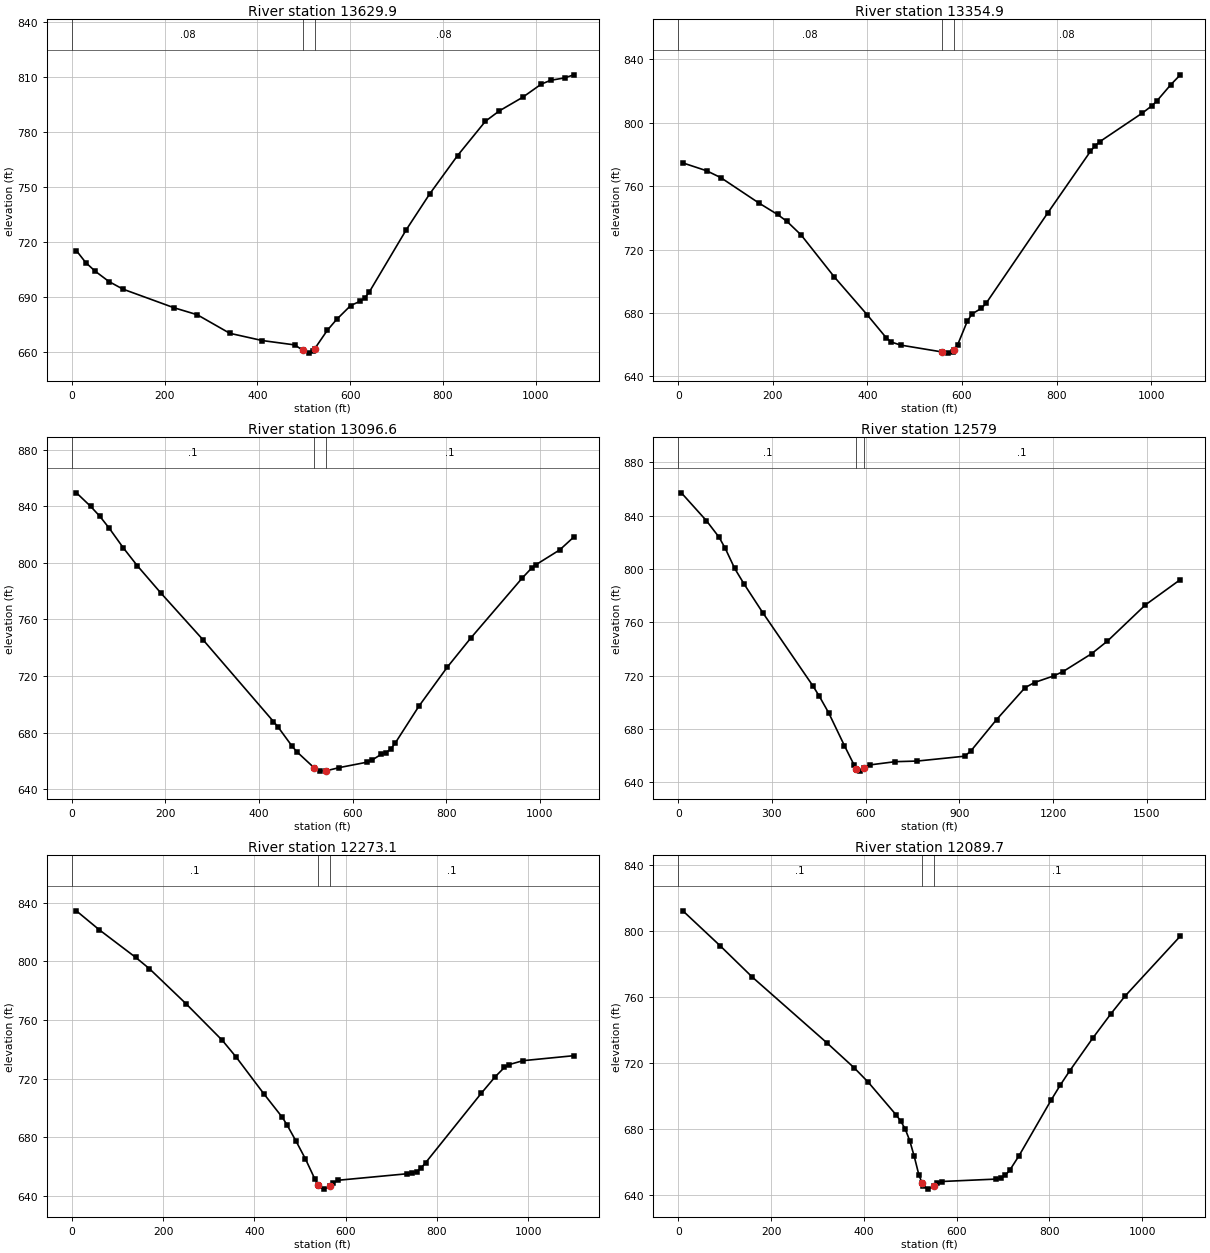
Type RM Length L Ch R = 1 ,13629.9 ,281.9,275,268
XS GIS Cut Line= 3
     1561536.669      445183.145     1561979.359      445437.577
     1562471.819      445726.918
#Sta/Elev= 30
      10  715.44      30  708.98    50.1  704.32    80.1  698.62   110.1   694.5
   220.3  684.34   270.3  680.54   340.4  670.43   410.5  666.47   480.6  664.09
   498.1  661.12   510.6  659.62   520.6  660.98   523.1  661.89   550.7  672.09
   570.7  677.98   600.8  685.51   620.8  687.84   630.8  689.55   640.9  692.86
     721  726.95   771.1  746.31   831.3  767.26   891.4  785.97   921.4  791.61
   971.5  798.99  1011.6  806.16  1031.7  808.24  1061.7  809.55  1081.8  811.23
#Mann= 3 , 0 , 0
       0     .08       0   498.1    .045       0   523.1     .08       0
Bank Sta=498.1,523.1
XS Rating Curve= 0 ,0
Exp/Cntr=0.3,0.1

Type RM Length L Ch R = 1 ,13354.9 ,260.9,258.2,258.1
XS GIS Cut Line= 4
     1561422.373      445553.742     1561820.678       445650.72
     1562090.832      445730.381     1562454.502      445799.652
#Sta/Elev= 30
      10  774.66      60  769.73      90  765.39     170  749.48     210  742.14
     230  737.75     260  729.16     330  702.74   399.9  678.71   440.1  664.22
   450.2  661.66   470.3   659.7   558.4  655.34   570.9  654.62   580.9  655.43
   583.4  656.55     591  659.95   611.1  674.61   621.2  679.33   641.3  682.95
   651.4  686.22   781.6  743.17   871.7  781.96   881.7   785.5   891.7  788.14
   981.8  806.22  1001.8  810.78  1011.8  813.66  1041.8   824.1  1061.8  830.28
#Mann= 3 , 0 , 0
       0     .08       0   558.4    .045       0   583.4     .08       0
Bank Sta=558.4,583.4
XS Rating Curve= 0 ,0
Exp/Cntr=0.3,0.1

Type RM Length L Ch R = 1 ,13096.6 ,507.5,517.6,525.1
XS GIS Cut Line= 3
     1561321.931      445820.433      1561844.07      445916.642
      1562364.45      446066.342
#Sta/Elev= 30
      10  849.49    40.1  839.98    60.1  832.87    80.1  824.45   110.2  810.55
   140.2   797.9   190.3  778.69   280.5  745.61   430.8   687.9   440.8  683.93
   470.8  670.38   480.8  666.52   518.4  654.99   530.9  652.86   543.4  653.08
     571  655.33   631.2  659.21   641.2  660.65   661.3  664.79   671.3  665.95
   681.3  668.44   691.4  672.95   741.5  698.77   801.7  726.16   851.8  746.71
   962.1  789.27   982.2  796.33   992.2  798.85  1042.3  809.19  1072.4   818.3
#Mann= 3 , 0 , 0
       0      .1       0   518.4    .045       0   543.4      .1       0
Bank Sta=518.4,543.4
XS Rating Curve= 0 ,0
Exp/Cntr=0.3,0.1

Type RM Length L Ch R = 1 ,12579   ,304,306,308
XS GIS Cut Line= 4
     1561238.807      446121.759     1561727.603        446378.5
      1561996.77      446541.473      1562736.81      446517.327
#Sta/Elev= 30
      10  857.12    90.3   836.2   130.5   823.9   150.6  815.42   180.7  800.42
   210.8  788.71     271  767.09   431.7  712.12   451.7  704.52   481.9  691.97
     532  667.49   562.3  653.29   570.1  650.35   572.4  649.48   582.6  648.39
   595.1  650.77     613  653.04   694.2  655.47   765.3  655.95   917.5   659.6
   937.8  663.82  1018.9  687.01  1110.2     711  1140.6  714.86  1201.5  719.78
  1231.9  723.07  1323.2  736.46  1373.9  745.92  1495.6  773.09  1607.2  792.03
#Mann= 3 , 0 , 0
       0      .1       0   570.1    .045       0   595.1      .1       0
Bank Sta=570.1,595.1
XS Rating Curve= 0 ,0
Exp/Cntr=0.3,0.1

Type RM Length L Ch R = 1 ,12273.1 ,184.2,183.4,182.6
XS GIS Cut Line= 4
     1561093.339       446398.84     1561443.154      446547.772
     1561741.017      446759.046     1562052.734      446928.759
#Sta/Elev= 30
      10  834.39      60  821.53   140.1  802.66   170.1  794.97   250.1  771.18
   330.2  746.05   360.2  734.78   420.8  709.79   461.4  693.71   471.5  688.67
   491.8   677.3   512.1  665.35   532.4  651.87   540.1  647.86   542.5  646.61
   552.6  644.79   565.1  646.73   572.9  648.95   583.1  650.81   735.2  655.27
   745.4  655.63   755.5   656.7   765.7  659.22   775.8  662.92   897.5  710.13
   927.9  721.34   948.2  727.72   958.3  729.62   988.8   732.3  1100.3   735.7
#Mann= 3 , 0 , 0
       0      .1       0   540.1    .045       0   565.1      .1       0
Bank Sta=540.1,565.1
XS Rating Curve= 0 ,0
Exp/Cntr=0.3,0.1

Type RM Length L Ch R = 1 ,12089.7 ,187.1,187.2,187.2
XS GIS Cut Line= 4
     1560999.824      446565.089     1561425.837       446762.51
     1561654.429      446914.905     1561900.339      447146.961
#Sta/Elev= 30
      10  812.07    89.9     791   159.8  771.85   319.7  732.21   379.6  716.79
   409.6  708.16   469.5   688.4   479.3  684.73   489.2  679.82     499  672.79
   508.8  663.12   518.6  652.16   525.7     647   528.4  645.04   538.2  643.31
   550.7  645.25   557.8  646.73   567.7  647.93   685.4   649.4   695.2  649.88
     705  651.68   714.8  654.83   734.5  663.47   803.9  697.31   823.8  706.48
   843.7  714.93   893.4  734.79   933.2  749.79     963  760.28  1082.4  796.73
#Mann= 3 , 0 , 0
       0      .1       0   525.7    .045       0   550.7      .1       0
Bank Sta=525.7,550.7
XS Rating Curve= 0 ,0
Exp/Cntr=0.3,0.1

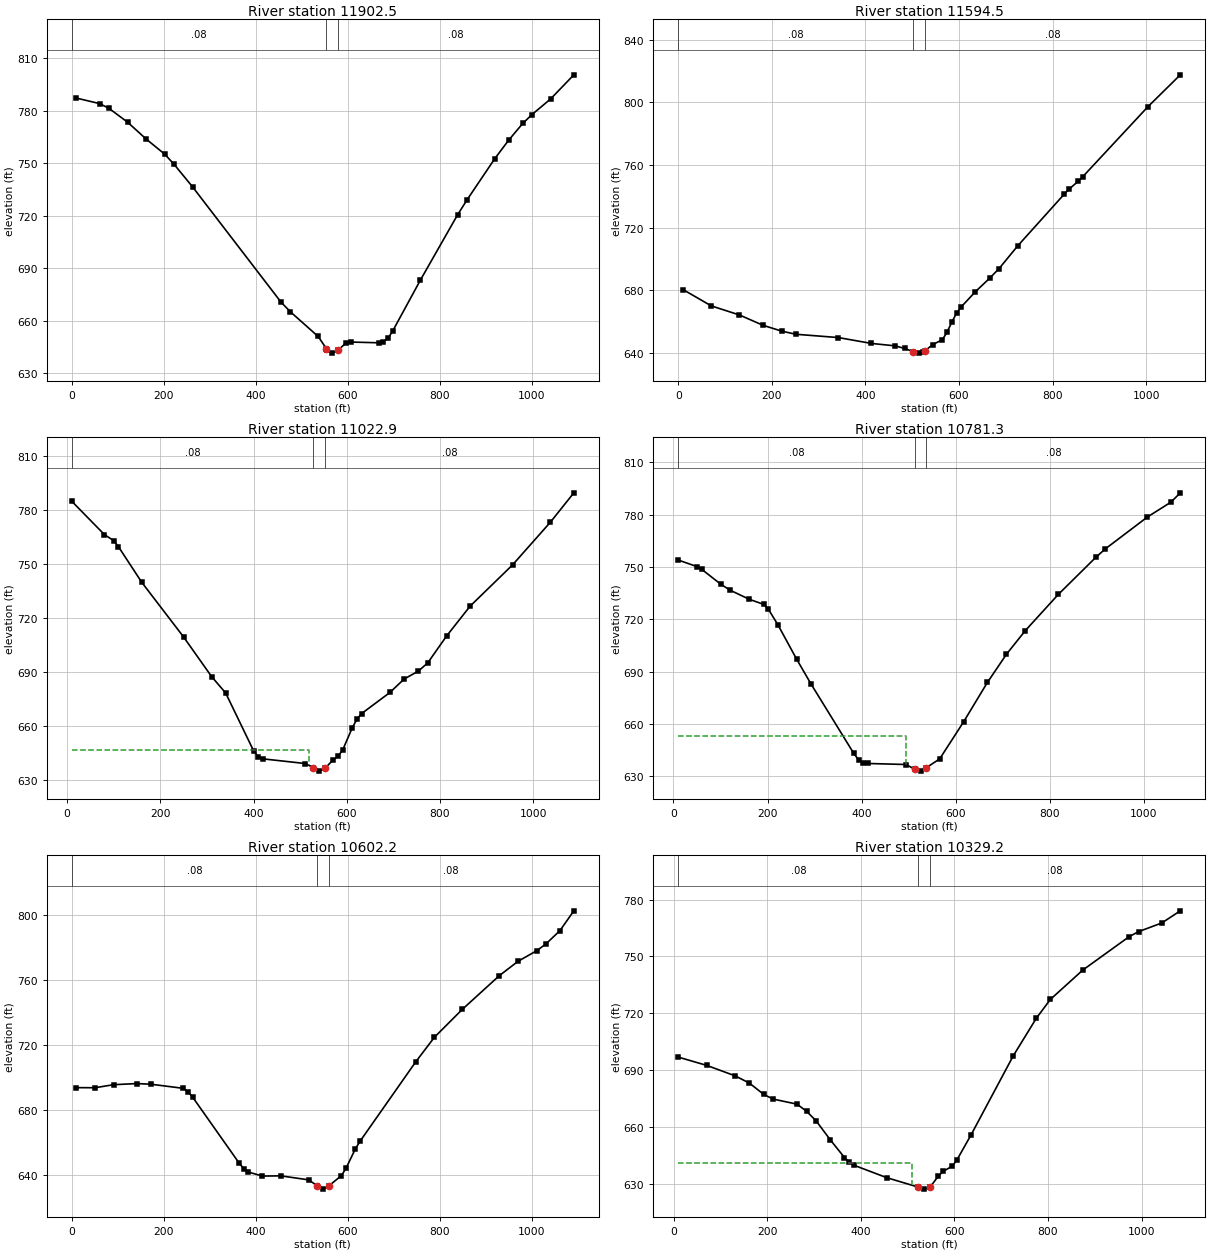
Type RM Length L Ch R = 1 ,11902.5 ,309.4,308.1,306.7
XS GIS Cut Line= 3
     1560904.763      446638.816     1561358.499      446942.526
     1561812.235      447246.236
#Sta/Elev= 30
    10.1  787.22    60.7  784.06    80.9  781.34   121.3  773.47   161.8   763.8
   202.2  755.15   222.4  749.39   262.9  736.41     455   670.6   475.2  665.11
   535.9  650.93   553.7  644.01   556.1  643.01   566.2  641.41   578.7  642.97
   596.6  647.28   606.7  647.75   667.3  647.32   677.4  647.85   687.6  649.82
   697.7  653.92   758.3  683.19   839.2  720.52   859.4  728.93   920.1  752.62
   950.4   763.2   980.8  772.71    1001  777.82  1041.4  786.72    1092  800.52
#Mann= 3 , 0 , 0
       0     .08       0   553.7    .045       0   578.7     .08       0
Bank Sta=553.7,578.7
XS Rating Curve= 0 ,0
Exp/Cntr=0.3,0.1

Type RM Length L Ch R = 1 ,11594.5 ,580.6,571.6,562.6
XS GIS Cut Line= 4
     1560708.888      447036.128     1561078.918      447133.261
     1561330.291      447284.085     1561668.283      447493.312
#Sta/Elev= 30
    10.1  680.57    70.5  670.15   130.9  664.33   181.2  657.75   221.5     654
   251.7  652.02   342.3  649.92   412.9  646.18   463.4  644.63   483.7  643.01
   501.5     641     514  639.99   524.1  640.71   526.5  641.26   544.3  645.48
   564.5  648.54   574.6  653.34   584.7  659.74   594.8  665.42     605  669.53
   635.3  679.22   665.6  687.76   685.7  693.89   725.4  708.34   824.8  741.33
   834.7  744.44   854.6  749.55   864.5  752.49  1003.7  797.13  1073.2  817.56
#Mann= 3 , 0 , 0
       0     .08       0   501.5    .045       0   526.5     .08       0
Bank Sta=501.5,526.5
XS Rating Curve= 0 ,0
Exp/Cntr=0.3,0.1

Type RM Length L Ch R = 1 ,11022.9 ,243.1,241.6,240.1
XS GIS Cut Line= 3
     1560445.304       447632.18     1560918.407      447714.529
     1561511.714      447842.618
#Sta/Elev= 30
      10  784.76      80  766.25     100   762.9     110  759.58   160.1  739.78
   250.1  709.35   310.1  687.39   340.2   678.3   400.2  646.17   410.2  642.83
   420.2  641.74   510.6  639.16   528.4  636.89   540.9  634.93   553.4  636.53
   571.3  641.29   581.4  643.18   591.5  646.82   611.7  658.95   621.8  663.73
     632  666.91   692.7  678.62     723  686.05   753.4  690.43   773.6  694.97
   814.1  709.92   864.6  726.51   955.7  749.43  1036.6  773.05  1087.2  789.44
#Mann= 3 , 0 , 0
      10     .08       0   528.4    .045       0   553.4     .08       0
#XS Ineff= 2 , 0
          519.21  646.69
Permanent Ineff=
       F       F
Bank Sta=528.4,553.4
XS Rating Curve= 0 ,0
Exp/Cntr=0.3,0.1

Type RM Length L Ch R = 1 ,10781.3 ,179.5,179.1,178.7
XS GIS Cut Line= 4
     1560428.343      447895.081     1560778.159      447940.106
     1561148.755      447998.986     1561495.107      448044.012
#Sta/Elev= 30
    10.1  753.94    50.4  750.13    60.5  748.52   100.8  740.03   120.9   736.6
   161.2  731.44   191.5  728.58   201.5  725.86   221.7  716.96     262  697.05
   292.2  683.01   383.1  643.24   393.3  639.54   403.4  637.82   413.6  637.44
   494.7  636.84   512.6  634.11   525.1  633.06   537.6  635.07   565.7  640.04
   616.4  661.19   667.1  683.81   707.7  699.99   747.9  713.56   817.8  734.22
   897.6  755.47   917.5  760.25  1007.4   778.6  1057.3  787.08  1077.2  792.42
#Mann= 3 , 0 , 0
    10.1     .08       0   512.6    .045       0   537.6     .08       0
#XS Ineff= 2 , 0
          493.54  653.15
Permanent Ineff=
       F       F
Bank Sta=512.6,537.6
XS Rating Curve= 0 ,0
Exp/Cntr=0.3,0.1

Type RM Length L Ch R = 1 ,10602.2 ,270.8,273,275.2
XS GIS Cut Line= 3
      1560384.64      448066.687     1560925.081      448144.403
     1561465.522      448222.118
#Sta/Elev= 30
    10.1  693.74    50.6  693.68      91  695.55   141.6  696.24   171.9  695.85
   242.7  693.31   252.8  691.24   262.9   687.9     364  647.37   374.1  643.95
   384.2  641.83   414.6   639.4     455  639.51   515.7  637.04   533.5  633.41
     546  631.36   558.5   633.2   586.4  639.65   596.6  644.26   616.8   656.1
   626.9  660.75   748.2  709.63   788.7  724.69   849.3  741.82   930.2  762.64
   970.7  771.41  1011.1  777.87  1031.3  782.06  1061.7  790.23    1092  802.42
#Mann= 3 , 0 , 0
       0     .08       0   533.5    .045       0   558.5     .08       0
Bank Sta=533.5,558.5
XS Rating Curve= 0 ,0
Exp/Cntr=0.3,0.1

Type RM Length L Ch R = 1 ,10329.2 ,448.9,453.8,460.1
XS GIS Cut Line= 4
     1560339.514      448318.864     1560720.501      448377.744
     1561042.609      448450.478     1561402.815      448519.749
#Sta/Elev= 30
    10.1     697      71  692.63   131.9   687.1   162.3  683.26   192.8  677.34
     213  674.87   263.8  672.22   284.1  668.48   304.4  663.49   334.8  653.44
   365.2  644.08   375.4  641.61   385.5  640.03   455.6  633.47   523.1  628.49
   535.6  627.45   548.1  628.54   565.6  634.29   575.6  636.77   595.6  639.58
   605.7  642.98   635.7   656.1   725.6  697.64   775.2  717.55     805   727.4
   874.3  742.87   973.5   760.5   993.3   763.1  1042.9  767.66  1082.5  774.06
#Mann= 3 , 0 , 0
    10.1     .08       0   523.1    .045       0   548.1     .08       0
#XS Ineff= 2 , 0
          509.45  641.34
Permanent Ineff=
       F       F
Bank Sta=523.1,548.1
XS Rating Curve= 0 ,0
Exp/Cntr=0.3,0.1

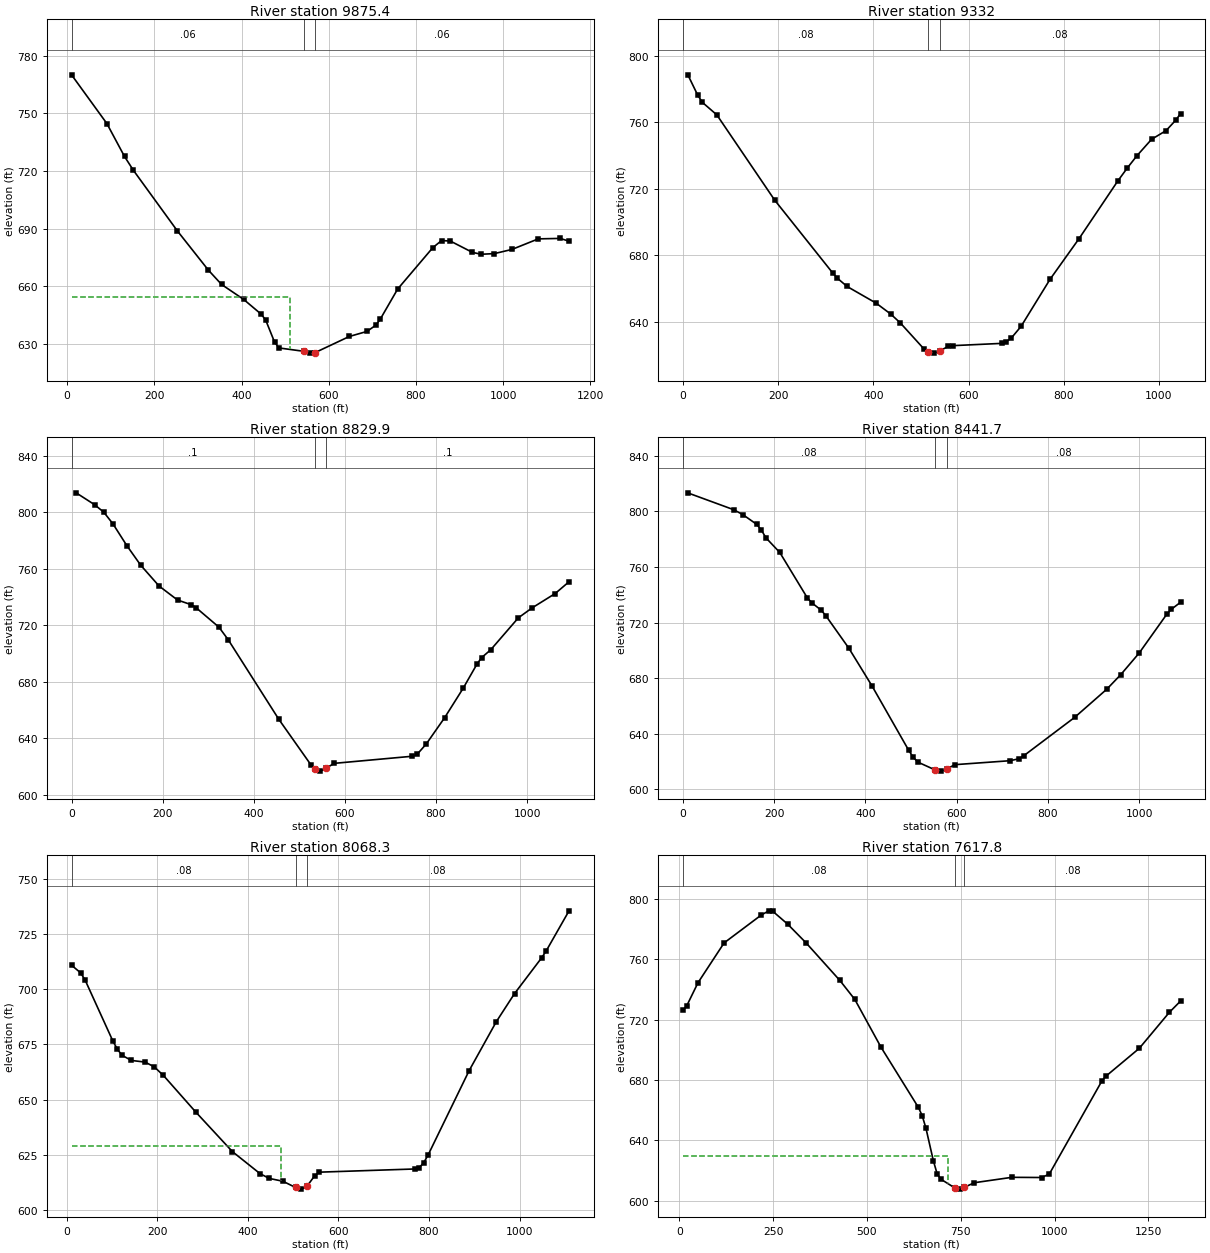
Type RM Length L Ch R = 1 ,9875.4  ,539.2,543.4,546.6
XS GIS Cut Line= 3
     1560204.353      448632.811     1560713.456       448831.67
     1561257.035      449096.363
#Sta/Elev= 30
    10.1  769.99    91.1  744.65   131.6   727.5   151.8  720.36     253  688.73
   323.9  668.38   354.3  660.89   404.9  653.13   445.3   645.4   455.5  642.35
   475.7  630.95   485.8  627.88   544.1  626.09   556.6  625.18   569.1   625.5
   647.3  633.85   687.6  636.46   707.8  639.67   717.9  642.72   758.2  658.55
   838.8  680.07   858.9  683.77   879.1  683.48   929.5  677.62   949.6  676.62
   979.9  676.97  1020.2  679.13  1080.6  684.63    1131  684.87  1151.2  683.42
#Mann= 3 , 0 , 0
    10.1     .06       0   544.1    .045       0   569.1     .06       0
#XS Ineff= 2 , 0
          511.94   654.5
Permanent Ineff=
       F       F
Bank Sta=544.1,569.1
XS Rating Curve= 0 ,0
Exp/Cntr=0.3,0.1

Type RM Length L Ch R = 1 ,9332    ,510.2,502.1,493.9
XS GIS Cut Line= 3
     1560022.038      449034.506     1560463.009       449304.84
     1560908.699      449588.669
#Sta/Elev= 30
    10.1  788.46    30.4  776.47    40.6   771.9      71  764.38   192.7  713.07
   314.4  669.37   324.5  666.13   344.8   661.2   405.7   651.2   436.1   644.7
   456.4  639.37   507.1   623.4   514.9  621.76   527.4  621.13   539.9  622.64
   557.9  625.18     568  625.64   669.7  626.99   679.8  628.11     690  630.23
   710.3  637.16   771.3  665.51   832.2  689.93   913.5  724.55   933.9  732.52
   954.2   739.9   984.7  749.69  1015.1   754.9  1035.5  761.18  1045.6  765.16
#Mann= 3 , 0 , 0
       0     .08       0   514.9    .045       0   539.9     .08       0
Bank Sta=514.9,539.9
XS Rating Curve= 0 ,0
Exp/Cntr=0.3,0.1

Type RM Length L Ch R = 1 ,8829.9  ,388.8,388.2,387.2
XS GIS Cut Line= 3
     1559698.341       449602.04     1560226.025      449742.245
     1560752.165      449888.321
#Sta/Elev= 30
    10.1  813.81    50.6   805.4    70.8  800.08      91  791.78   121.3  776.44
   151.7  762.58   192.1  747.78   232.6  737.87   262.9  734.51     273  732.52
   323.6   718.6   343.8  709.76     455  653.31   525.8  620.91   533.5  618.41
     546  616.61   558.5  618.59   576.3  622.11   748.2  627.16   758.3  628.42
   778.6  635.84     819  654.49   859.5  675.26   889.8  692.37   899.9  696.98
   920.1  702.59   980.8  725.25  1011.1  732.31  1061.7  742.47    1092   750.8
#Mann= 3 , 0 , 0
       0      .1       0   533.5    .045       0   558.5      .1       0
Bank Sta=533.5,558.5
XS Rating Curve= 0 ,0
Exp/Cntr=0.3,0.1

Type RM Length L Ch R = 1 ,8441.7  ,375.9,373.4,370.6
XS GIS Cut Line= 2
     1559613.442      449992.133     1560674.145      450246.485
#Sta/Elev= 30
    10.1  813.33   111.1  801.18   131.3   797.6   161.6  790.62   171.7  786.51
   181.8  780.94   212.1  770.41   272.7  737.63   282.8  734.05     303  728.87
   313.1  724.88   363.6  701.49   414.1  674.49   494.9  627.97     505  622.88
   515.1  619.52   553.1  613.87   565.6  613.07   578.1  614.58   595.9  617.72
   717.1  620.57   737.3  622.03   747.4  624.22   858.5  651.71   929.2  672.06
   959.5  682.42   999.9  697.96  1060.5  725.91  1070.6  729.52  1090.8  734.59
#Mann= 3 , 0 , 0
       0     .08       0   553.1    .045       0   578.1     .08       0
Bank Sta=553.1,578.1
XS Rating Curve= 0 ,0
Exp/Cntr=0.3,0.1

Type RM Length L Ch R = 1 ,8068.3  ,470.7,450.5,430.8
XS GIS Cut Line= 3
     1559543.089      450370.956     1560029.675      450474.898
     1560636.263      450554.955
#Sta/Elev= 30
    10.2  710.82    30.5  707.32    40.6  703.92   101.5   676.5   111.7   672.7
   121.9  670.04   142.2  667.72   172.6  666.97   192.9  664.82   213.2  660.92
   284.3  644.44   365.6  626.46   426.5  616.51   446.8  614.33   477.3  613.03
   505.1  610.22   517.6  609.47   530.1  610.71   547.7  615.59   557.7  617.15
   768.4  618.59   778.4  619.19   788.4  621.44   798.5  625.12   888.7  663.12
   948.9  685.31     989  697.98  1049.2  714.25  1059.3  717.42  1109.4  735.43
#Mann= 3 , 0 , 0
    10.2     .08       0   505.1    .045       0   530.1     .08       0
#XS Ineff= 2 , 0
          473.34  628.82
Permanent Ineff=
       F       F
Bank Sta=505.1,530.1
XS Rating Curve= 0 ,0
Exp/Cntr=0.3,0.1

Type RM Length L Ch R = 1 ,7617.8  ,564.3,587.9,613.9
XS GIS Cut Line= 4
     1559456.501      450982.483     1559932.735      451020.366
     1560322.381      450760.602     1560706.615      450695.661
#Sta/Elev= 30
      10  726.17    19.9  729.12    49.8  744.37   119.4  770.75     219  789.32
   238.9  791.99   248.8  791.75   288.6  783.21   338.4  770.62     428  745.85
   467.8  733.28   537.5  701.67   637.2  661.76   647.1   656.4   657.1  648.18
     677  626.47     687  617.89   696.9  614.28   734.3  608.45   746.8  607.68
   759.3   608.9   786.6  611.94   886.3   615.5     966  615.37     986  617.67
  1125.9  679.23  1135.9  682.28  1225.8  700.93  1305.7  724.71  1335.7  732.24
#Mann= 3 , 0 , 0
      10     .08       0   734.3    .045       0   759.3     .08       0
#XS Ineff= 2 , 0
          716.26  629.72
Permanent Ineff=
       F       F
Bank Sta=734.3,759.3
XS Rating Curve= 0 ,0
Exp/Cntr=0.3,0.1

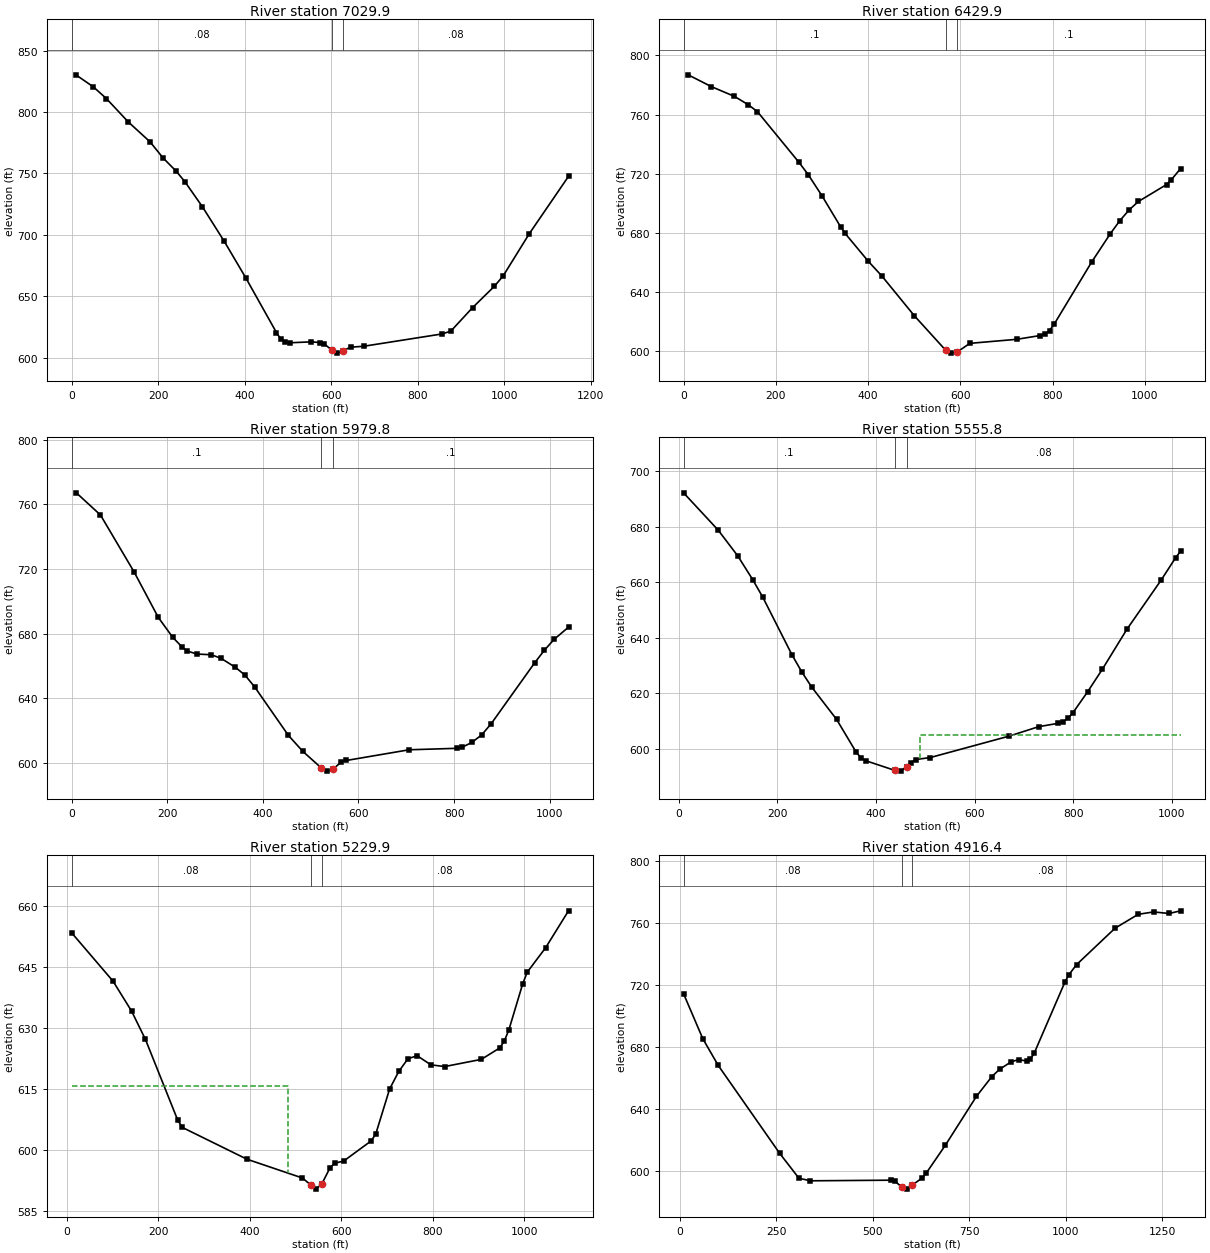
Type RM Length L Ch R = 1 ,7029.9  ,611,600,586.3
XS GIS Cut Line= 3
     1559640.103      451262.241      1560232.11      451427.005
     1560731.007      451617.168
#Sta/Elev= 30
    10.1  830.41    50.4  820.61    80.6  811.06     131  792.07   181.3  775.85
   211.6  762.66   241.8  751.89   261.9  743.35   302.2  723.02   352.6   694.9
     403  664.76   473.5  620.42   483.5  615.08   493.6  612.63   503.7  612.04
   554.1   612.8   574.2  612.22   584.3     611     602  605.95   614.5  603.61
     627   605.5   644.7  608.47     675  609.19   856.3  619.25   876.4  621.53
   926.8  640.71   977.2  658.12   997.3  666.49  1057.8  700.96  1148.4  747.67
#Mann= 3 , 0 , 0
       0     .08       0     602    .045       0     627     .08       0
Bank Sta=602,627
XS Rating Curve= 0 ,0
Exp/Cntr=0.3,0.1

Type RM Length L Ch R = 1 ,6429.9  ,428.9,450.1,471.4
XS GIS Cut Line= 3
      1559588.05      452002.555     1560174.171      451931.885
     1560657.585      451872.326
#Sta/Elev= 30
      10   786.9      60  778.95   110.1  772.32   140.1  766.68   160.1  761.95
   250.2  727.59   270.2  719.29   300.2  704.86   340.2  684.05   350.2  679.45
   400.2  660.65   430.3  650.44   500.3  623.65   567.9   600.4   580.4  598.34
   592.9  599.08   620.8  604.97   722.3   607.7     773  610.26   783.2  611.15
   793.3  613.65   803.5  618.01   884.6  660.03   925.2  679.28   945.5  687.98
   965.8  695.35   986.1  701.09    1047  712.55  1057.1  715.71  1077.4  723.35
#Mann= 3 , 0 , 0
       0      .1       0   567.9    .045       0   592.9      .1       0
Bank Sta=567.9,592.9
XS Rating Curve= 0 ,0
Exp/Cntr=0.3,0.1

Type RM Length L Ch R = 1 ,5979.8  ,435,424,413
XS GIS Cut Line= 3
     1559635.154      452038.575     1560022.811      452327.807
     1560466.362      452662.273
#Sta/Elev= 30
    10.1   767.1    60.5  753.41     131  718.12   181.4  690.09   211.6  677.79
   231.8  671.58   241.8  669.33     262  667.44   292.2  666.99   312.4  664.84
   342.6  659.23   362.7   654.4   382.9  647.11   453.4  617.17   483.7  607.25
   521.7  597.18   534.2  595.05   546.7  596.22   564.5  600.84   574.6  601.63
   705.9  608.25   806.9  609.16     817  609.83   837.2  612.82   857.4  617.38
   877.6  624.38   968.5  662.04   988.7  669.78  1008.9  676.46  1039.2  684.07
#Mann= 3 , 0 , 0
       0      .1       0   521.7    .045       0   546.7      .1       0
Bank Sta=521.7,546.7
XS Rating Curve= 0 ,0
Exp/Cntr=0.3,0.1

Type RM Length L Ch R = 1 ,5555.8  ,333.6,325.9,318.1
XS GIS Cut Line= 4
     1559406.995      452543.816       1559658.1      452643.392
      1560017.44       452734.31     1560394.098      452751.627
#Sta/Elev= 30
      10  692.26      80  678.86   120.1  669.48   150.1     661   170.1  654.83
   230.1  633.79   250.1   627.6   270.1  622.19   320.2  610.64   360.3  598.71
   370.3  596.71   380.3  595.67     438  592.26   450.5  591.97     463  593.62
   470.5  594.99   480.5  596.13   510.6  596.88   670.6  604.61   730.1  607.99
   769.8   609.2   779.7  609.75   789.6  610.99   799.6  613.02   829.3  620.56
   859.1  628.65   908.7  643.01   978.2  660.75  1007.9  668.92  1017.8  671.21
#Mann= 3 , 0 , 0
      10      .1       0     438    .045       0     463     .08       0
#XS Ineff= 2 , 0
                          489.69          605.07
Permanent Ineff=
       F       F
Bank Sta=438,463
XS Rating Curve= 0 ,0
Exp/Cntr=0.3,0.1

Type RM Length L Ch R = 1 ,5229.9  ,312.4,313.5,314.7
XS GIS Cut Line= 3
     1559269.089      453029.032     1559813.814      453012.117
     1560364.957      452993.416
#Sta/Elev= 30
    10.1  653.42   100.9  641.47   141.3  634.13   171.6  627.17   242.2  607.29
   252.3  605.49   393.6  597.67   514.7  593.05   532.5   591.4     545  590.31
   557.5  591.66   575.1  595.55   585.1  596.68   605.1  597.23   665.3   602.2
   675.3  603.95   705.4  614.96   725.5  619.29   745.5   622.4   765.6  623.13
   795.7  620.89   825.7  620.47   905.9  622.24     946  625.05   956.1  626.76
   966.1  629.53   996.2   640.8  1006.2   643.7  1046.3   649.7  1096.4  658.79
#Mann= 3 , 0 , 0
    10.1     .08       0   532.5    .045       0   557.5     .08       0
#XS Ineff= 2 , 0
          482.74  615.64
Permanent Ineff=
       F       F
Bank Sta=532.5,557.5
XS Rating Curve= 0 ,0
Exp/Cntr=0.3,0.1

Type RM Length L Ch R = 1 ,4916.4  ,1021.8,1031.6,1041.4
XS GIS Cut Line= 4
     1559277.113      453357.743     1559623.464      453318.779
     1560142.992      453323.108     1560571.603      453336.096
#Sta/Elev= 30
      10  714.32    59.7  685.32    99.6  668.03   258.9  611.16   308.7   595.1
   338.6  593.43   548.4  593.83  557.35  593.22   575.8  589.17   588.3  588.05
   600.8  590.45   628.3  595.33   638.3  598.36   688.2  616.54   768.2  647.94
   808.1  660.72   828.1  665.45   858.1  670.29   878.1   671.8     898  670.79
     908  671.91   917.9  675.89   997.7  721.99  1007.7  726.59  1027.6  733.12
  1127.4  756.69  1187.2  765.63  1227.1  767.18    1267  766.17  1296.9  767.89
#Mann= 3 , 0 , 0
      10     .08       0   575.8    .045       0   600.8     .08       0
Bank Sta=575.8,600.8
XS Rating Curve= 0 ,0
Exp/Cntr=0.3,0.1