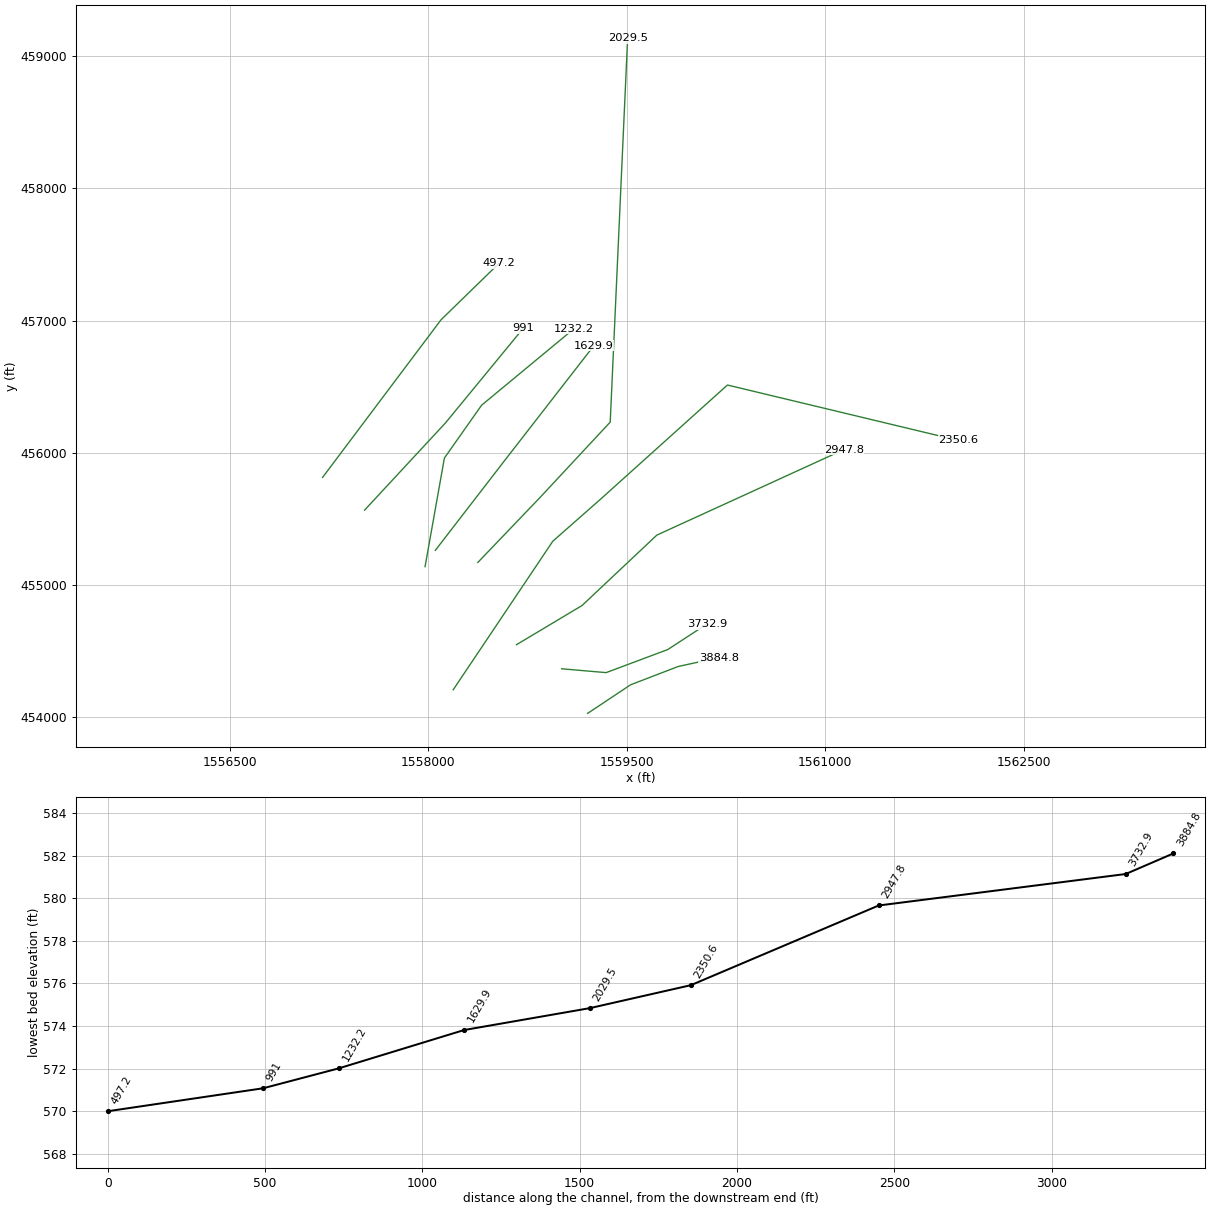
HEC-RAS study WILSONCR.prj: WILSONCR

--- WILSONCR.g01 (geometry) --- (continued)

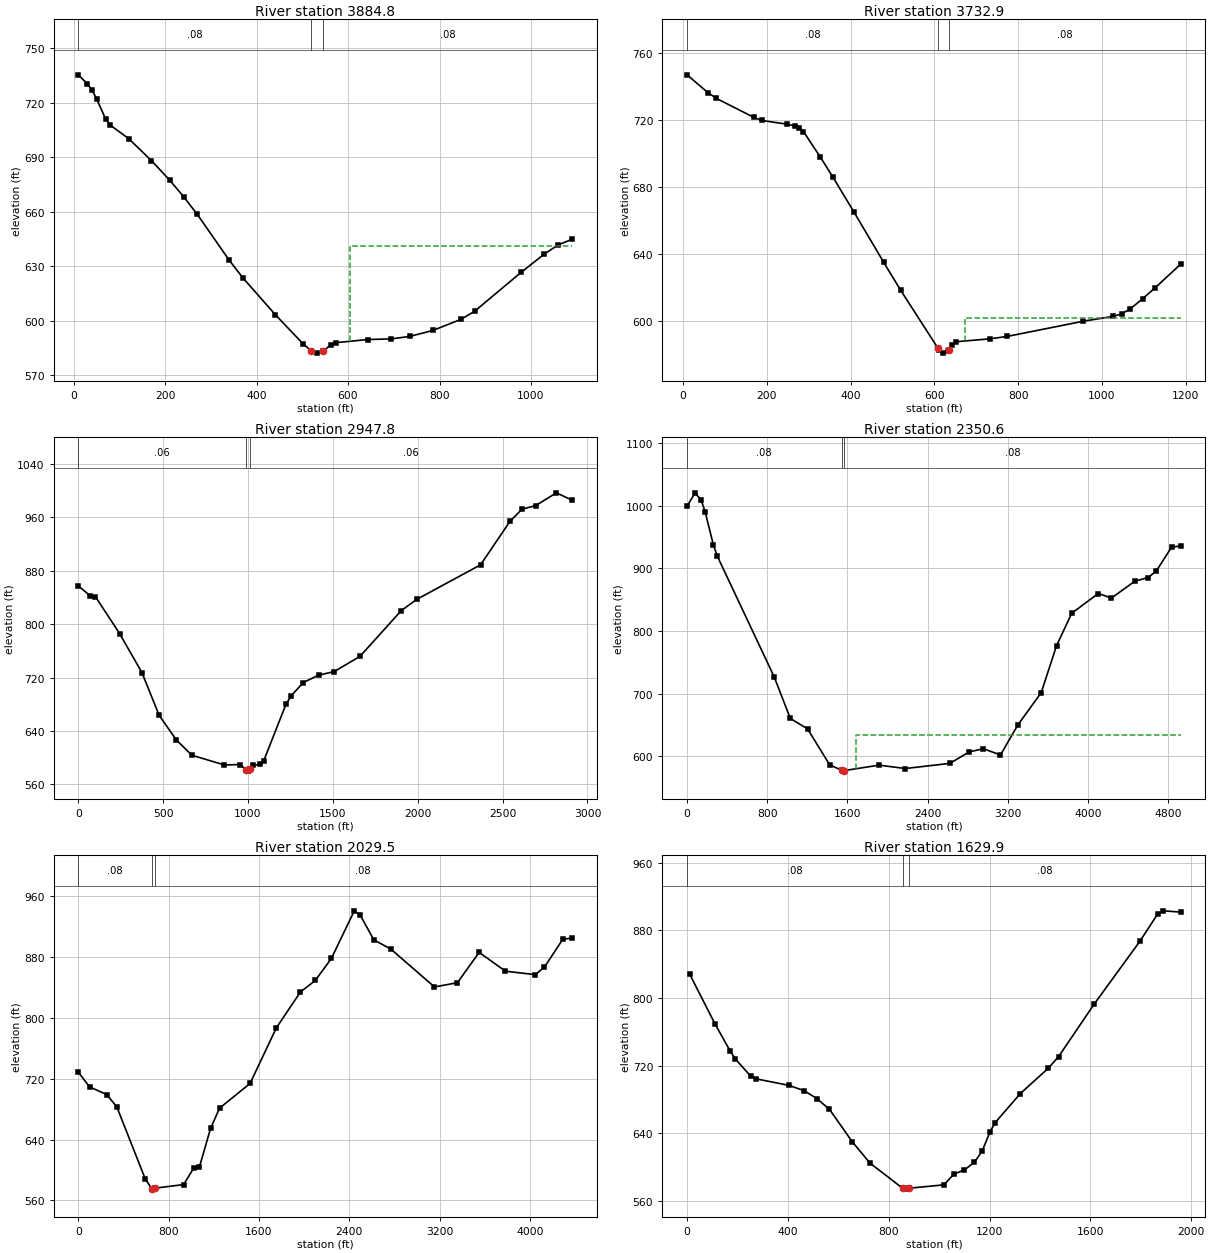
Type RM Length L Ch R = 1 ,3884.8  ,152.2,151.9,151.5
XS GIS Cut Line= 4
     1559203.513      454024.471     1559528.218      454240.941
     1559887.558      454379.481     1560194.487      454446.505
#Sta/Elev= 30
      10  735.34      30  730.38      40  726.97      50  722.21      70  710.97
    80.1  707.61   120.1  700.26   170.1  688.11   210.1  677.32   240.2  668.33
   270.2  658.55   340.2  633.25   370.2  623.52   440.9   603.3   501.7  587.22
   519.6  583.38   532.1  582.12   544.6  583.05   562.5   586.7   572.7  587.87
   643.6  589.61   694.3  589.96   734.8  591.31   785.5  594.61   846.3  600.66
   876.7  605.16   978.1  626.53  1028.7  636.59  1059.1  641.64  1089.5  644.78
#Mann= 3 , 0 , 0
      10     .08       0   519.6    .045       0   544.6     .08       0
#XS Ineff= 2 , 0
                          604.57          640.95
Permanent Ineff=
       F       F
Bank Sta=519.6,544.6
XS Rating Curve= 0 ,0
Exp/Cntr=0.3,0.1

Type RM Length L Ch R = 1 ,3732.9  ,758.9,785.1,810.5
XS GIS Cut Line= 4
     1559007.075      454362.218     1559343.121      454333.112
     1559808.823       454507.75     1560104.633      454700.976
#Sta/Elev= 30
     9.9   746.8    59.5  736.26    79.4  732.84   168.7  721.56   188.5  719.62
     248  717.46   267.9  716.32   277.8  715.43   287.7  713.06   327.4  698.06
   357.6   686.1   408.4  665.08   479.4  635.11     520  618.46     609  583.96
   611.4  583.04   621.5  581.15   631.7  582.26     634  583.07   641.8   585.8
     652  587.94   733.2  589.67   773.8  591.09   955.8  600.15  1026.5  603.01
  1046.7  604.48  1066.9  607.35  1097.1  613.53  1127.4  620.14    1188  634.13
#Mann= 3 , 0 , 0
     9.9     .08       0     609    .045       0     634     .08       0
#XS Ineff= 2 , 0
                          674.01          602.17
Permanent Ineff=
       F       F
Bank Sta=609,634
XS Rating Curve= 0 ,0
Exp/Cntr=0.3,0.1

Type RM Length L Ch R = 1 ,2947.8  ,614.2,597.2,580.3
XS GIS Cut Line= 4
     1558665.527      454544.442     1559161.597      454841.714
     1559726.591      455374.727     1561138.653       456021.71
#Sta/Elev= 30
       0  857.39      71  842.38   101.5  841.15   243.5   785.9   375.4  727.26
   476.9  663.18   578.3  626.38   669.1  603.54   860.8  588.92   951.6  589.56
   989.5   581.9    1002  579.67  1014.5  582.19  1032.3  588.28  1072.6  589.88
  1092.8  595.26  1223.9  679.91  1254.2  692.37  1324.8  712.36    1416  723.56
  1507.3  728.78  1659.6  751.66  1903.3  820.31  1994.6  837.18  2370.2   888.9
  2542.8  953.87  2613.9  972.24  2695.1  977.73  2816.9   996.8  2908.3  985.89
#Mann= 3 , 0 , 0
       0     .06       0   989.5    .045       0  1014.5     .06       0
Bank Sta=989.5,1014.5
XS Rating Curve= 0 ,0
Exp/Cntr=0.3,0.1

Type RM Length L Ch R = 1 ,2350.6  ,318.7,321.1,323.5
XS GIS Cut Line= 5
     1558187.558      454203.701      1558940.13       455328.33
      1559300.05      455645.907     1560260.136      456511.444
     1562007.521      456091.307
#Sta/Elev= 30
       0  999.39    80.8 1020.84   141.4 1009.08   181.8  989.97   262.6  937.59
     303  919.21   868.5  726.83    1030  660.06  1201.7  643.54  1423.2   585.8
  1540.7  577.48  1553.2  575.92  1565.7  576.74    1914  585.46  2176.6   580.1
  2620.9  588.29  2812.8   606.6  2954.2  611.77  3125.8  601.76  3298.4  649.69
    3532   701.4  3684.3  776.42  3836.6  828.42  4100.6  859.86  4232.6  852.66
  4466.1  879.62  4598.1  885.45  4679.3  895.82  4831.6     934    4923  935.82
#Mann= 3 , 0 , 0
       0     .08       0  1540.7    .045       0  1565.7     .08       0
#XS Ineff= 2 , 0
                         1684.35          634.17
Permanent Ineff=
       F       F
Bank Sta=1540.7,1565.7
XS Rating Curve= 0 ,0
Exp/Cntr=0.3,0.1

Type RM Length L Ch R = 1 ,2029.5  ,396.8,399.6,402.3
XS GIS Cut Line= 5
     1558373.587      455167.669     1558845.808      455661.942
     1559117.308      455954.164     1559374.111      456230.568
       1559505.8      459137.296
#Sta/Elev= 30
       0  728.51   100.5   709.1   251.3  699.09   341.8  682.83   593.1  588.23
     651  575.37   663.5  574.84     676  576.05   932.9  580.81  1022.6  602.62
  1072.5  603.86  1171.8  654.84  1251.3  681.22  1520.6  713.56  1753.8  786.71
  1966.7  833.74  2098.5  848.95  2240.4  877.72  2443.2  940.32  2493.9  935.32
  2615.5  902.28  2767.6  889.97  3152.9  840.35  3355.6   845.9  3548.3  885.72
  3781.4  861.05    4045   856.5  4126.2  866.46  4288.4  902.88  4369.5  904.53
#Mann= 3 , 0 , 0
       0     .08       0     651    .045       0     676     .08       0
Bank Sta=651,676
XS Rating Curve= 0 ,0
Exp/Cntr=0.3,0.1

Type RM Length L Ch R = 1 ,1629.9  ,396.4,397.7,399.1
XS GIS Cut Line= 3
     1558052.434      455259.499     1558581.665      455946.702
     1559249.783      456808.612
#Sta/Elev= 30
    10.1  828.56   110.9  769.44   171.5  737.05   191.6  727.93   252.1  707.66
   272.3  704.47   403.4  696.71   463.9  690.42   514.4  681.07   564.8  668.34
   655.6  629.74   726.2  604.45   854.9   574.9   867.4  573.81   879.9  574.86
  1018.8  578.88  1059.2  591.89  1099.6   596.3    1140  605.92  1170.3  618.72
  1200.6  640.93  1220.8   652.1  1321.8  686.93  1432.8  716.95  1473.2  730.57
  1614.6  792.83  1796.3  867.42    1867  899.82  1887.2  903.28  1957.9  901.78
#Mann= 3 , 0 , 0
       0     .08       0   854.9    .045       0   879.9     .08       0
Bank Sta=854.9,879.9
XS Rating Curve= 0 ,0
Exp/Cntr=0.3,0.1

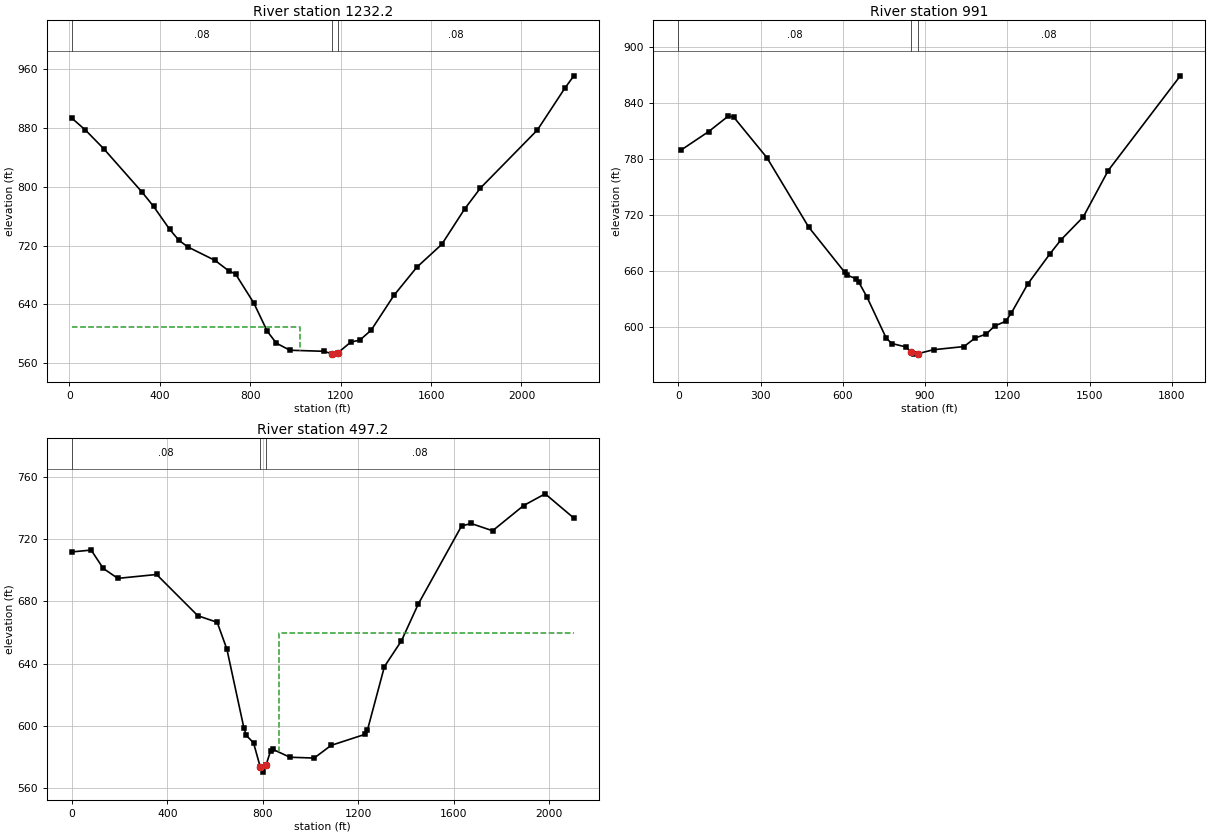
Type RM Length L Ch R = 1 ,1232.2  ,245.4,241.2,221.2
XS GIS Cut Line= 4
      1557974.64      455135.706     1558120.757      455958.291
     1558402.168      456358.761     1559100.284      456937.818
#Sta/Elev= 30
    10.1   893.7    70.5  877.45     151  852.15   322.1   792.5   372.4  773.27
   442.9  742.26   483.2   727.5   523.4  718.18   644.2  699.74   704.6  685.55
   734.8  681.23   815.3  641.87   875.4  603.12   915.4  586.98   975.3  577.31
  1125.1  575.88  1162.6  572.45  1175.1  572.01  1187.6  573.79    1245  588.44
    1285  591.15    1335  604.67  1435.8  652.12  1536.6  690.34  1647.4  721.63
  1748.2  769.67  1818.7  798.45  2070.7  877.58  2191.6  934.32  2231.9  951.37
#Mann= 3 , 0 , 0
    10.1     .08       0  1162.6    .045       0  1187.6     .08       0
#XS Ineff= 2 , 0
         1019.14  609.06
Permanent Ineff=
       F       F
Bank Sta=1162.6,1187.6
XS Rating Curve= 0 ,0
Exp/Cntr=0.3,0.1

Type RM Length L Ch R = 1 ,991     ,497.3,493.8,506.2
XS GIS Cut Line= 3
     1557517.511      455563.862     1558129.078      456224.635
      1558718.92      456943.858
#Sta/Elev= 30
    10.1  789.52   111.3  809.44   182.1  825.86   202.3  824.84   323.7  781.26
   475.5  707.13     607  658.69   617.1   655.5   647.4  651.89   657.6  648.46
   687.9   632.3   758.7  587.95     779  582.43   829.5  578.79   847.4   573.7
   859.9  571.07   872.4  571.46   930.7  575.79  1041.9  579.17  1082.3  588.33
  1122.8  592.55  1153.1  601.06  1193.6  606.24  1213.8  614.74  1274.4   646.2
  1355.3   678.5  1395.8  693.61  1476.6   717.9  1567.6  767.64  1830.5  869.05
#Mann= 3 , 0 , 0
       0     .08       0   847.4    .045       0   872.4     .08       0
Bank Sta=847.4,872.4
XS Rating Curve= 0 ,0
Exp/Cntr=0.3,0.1

Type RM Length L Ch R = 1 ,497.2   ,503.7,497.2,490.8
XS GIS Cut Line= 3
     1557200.111      455811.797     1558095.572      457005.746
     1558532.643      457432.156
#Sta/Elev= 30
       0  711.94    81.2  713.13     132  701.29   192.9  694.89   355.3  697.39
   527.9  670.82   609.2  666.56   649.8  649.22   720.8  598.61     731  593.68
   761.4  588.85   789.6  573.22   802.1  569.99   814.6  574.89   832.5  583.61
   842.7  584.67   913.7  579.59  1015.3  579.06  1086.3  587.23  1228.5  594.36
  1238.6  597.15  1309.7  638.06  1380.8   654.6  1451.8  678.44  1632.6  728.61
  1672.6  730.29  1762.7  725.58  1892.8  741.85  1982.9  749.39  2103.1  733.76
#Mann= 3 , 0 , 0
       0     .08       0   789.6    .045       0   814.6     .08       0
#XS Ineff= 2 , 0
                          866.12          659.89
Permanent Ineff=
       F       F
Bank Sta=789.6,814.6
XS Rating Curve= 0 ,0
Exp/Cntr=0.3,0.1

Chan Stop Cuts=-1
Use User Specified Reach Order=0